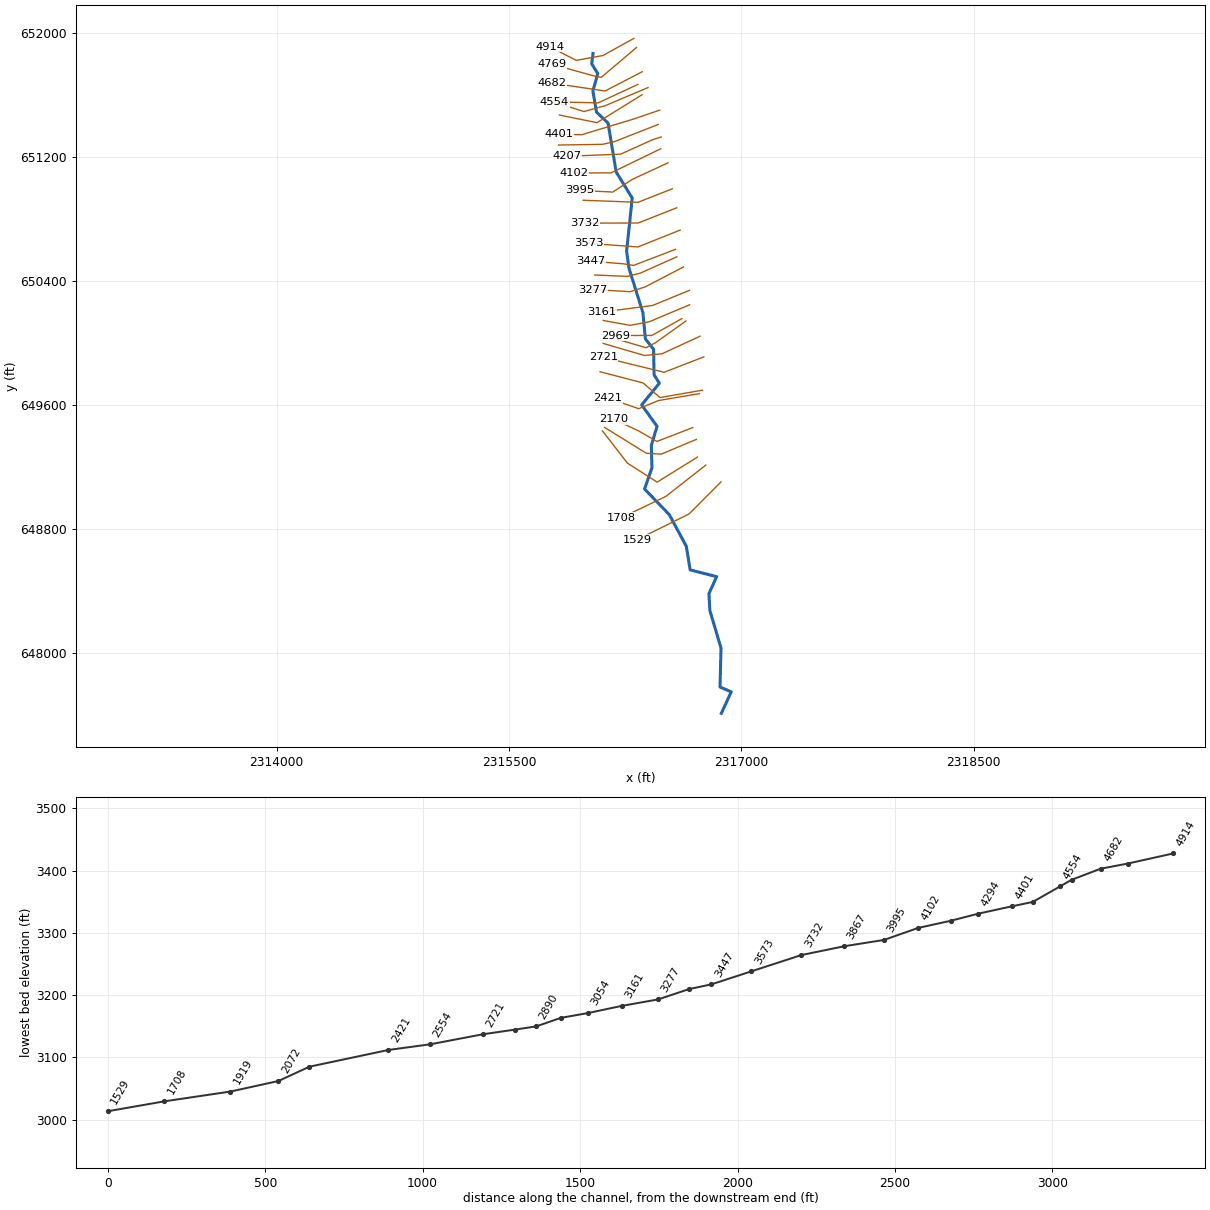
--- FALLRN.prj (project) ---

Proj Title=FALLRN
Current Plan=p01
Default Exp/Contr=0,0
English Units
Geom File=g01
Flow File=f01
Plan File=p01
BEGIN DESCRIPTION:
----------MODEL BY WOOD PLC 2022----------
AFH study
Randolph County, WV
HEC-RAS Version: RAS 6.2
Vertical Datum: NAVD88
Projection: NAD 1983 StatePlane West Virginia S FIPS 4702 (US Feet)
Terrain: 1-meter LIDAR (FEMA Region III 3DEP collected 2016-2018)
Land Use: 2019 NLCD
Hydrologic Method:
WV SIR2010-5033 regression equations
Additional Model Notes:
None
END DESCRIPTION:
DSS Export Rating Curves= 0
DSS Export Rating Curve Sorted= 0
DSS Export Volume Flow Curves= 0
DXF OffsetX= 0
DXF OffsetY= 0
DXF ScaleX= 0
DXF ScaleY= 0

--- FALLRN.p01 (plan) ---

Plan Title=Floodplain
Program Version=6.20
Short Identifier=Floodplain
Geom File=g01
Flow File=f01
Subcritical Flow
K Sum by GR= 0
Std Step Tol= 0.01
Critical Tol= 0.01
Num of Std Step Trials= 20
Max Error Tol= 0.3
Flow Tol Ratio= 0.001
Split Flow NTrial= 30
Split Flow Tol= 0.02
Split Flow Ratio= 0.02
Log Output Level= 0
Friction Slope Method= 1
Unsteady Friction Slope Method= 2
Unsteady Bridges Friction Slope Method= 1
Parabolic Critical Depth
Global Vel Dist= 0 , 0 , 0
Global Log Level= 0
CheckData=True
Encroach Param=-1 ,0,0, 0
Mapping Interval=1HOUR
Computation Time Step Use Courant=        0
Computation Time Step Use Time Series=    0
Computation Time Step Count To Double=0
Computation Time Step Max Doubling=0
Computation Time Step Max Halving=0
Computation Time Step Residence Courant=0
Run HTab= 0
Run UNet= 0
Run Sediment= 0
Run PostProcess= 0
Run WQNet= 0
Run RASMapper=-1
UNET Theta= 0
UNET Theta Warmup= 0
UNET ZTol= 0
UNET ZSATol= 0
UNET MxIter= 0
UNET Max Iter WO Improvement= 0
UNET MaxInSteps= 0
UNET DtIC= 0
UNET DtMin= 0
UNET MaxCRTS= 0
UNET WFStab= 0
UNET SFStab= 0
UNET WFX= 1
UNET SFX= 1
UNET Gravity=32.174
UNET 1D Methodology=Finite Difference
UNET DSS MLevel= 1
UNET Pardiso=0
UNET DZMax Abort= 0
UNET Use Existing IB Tables= 0
UNET Froude Reduction=False
UNET Froude Limit= 0
UNET Froude Power= 0
UNET D1 Cores= 0
UNET WindReference=Eulerian
UNET WindDragFormulation=Hsu (1988)
UNET D2 Coriolis=0
UNET D2 Cores= 0
UNET D2 Theta= 1
UNET D2 Theta Warmup= 1
UNET D2 Z Tol= 0.01
UNET D2 Volume Tol= 0.01
UNET D2 Max Iterations= 20
UNET D2 Equation= 0
UNET D2 RampUpFraction=0.1
UNET D2 TimeSlices= 1
UNET D2 Turbulence Formulation=Non-Conservative (original)
UNET D2 Eddy Viscosity=0.3
UNET D2 Transverse Eddy Viscosity=0.1
UNET D2 Smagorinsky Mixing=0
UNET D2 BCVolumeCheck=0
UNET D2 Cores=0
UNET D2 SolverType=PARDISO (Direct)
UNET D2 Minimum Iterations= 2147483647
UNET D2 Maximum Iterations= 2147483647
UNET D2 Restart Number= 10
UNET D2 Relaxation Coeff=1.3
UNET D2 SOR Precondition Iterations= 10
UNET D2 ILUT Maximum Fill= 8
UNET D2 ILUT Tolerance=1E-08
UNET D1D2 MaxIter= 0
UNET D1D2 ZTol=0.01
UNET D1D2 QTol=0.1
UNET D1D2 MinQTol=1
Write IC File= 0
Write IC File at Fixed DateTime=0
Write IC File at Sim End=0
Echo Input=False
Echo Parameters=False
Echo Output=False
Write Detailed= 0
HDF Write Warmup=0
HDF Write Time Slices=0
HDF Flush=0
HDF Compression= 1
HDF Chunk Size= 1
HDF Spatial Parts= 1
HDF Use Max Rows=0
HDF Fixed Rows= 1
Calibration Method= 0
Calibration Iterations= 20
Calibration Max Change=0.05
Calibration Tolerance=0.2
Calibration Maximum=1.5
Calibration Minimum=0.5
Calibration Optimization Method= 1
WQ AD Non Conservative
WQ ULTIMATE=-1
WQ Max Comp Step=1HOUR
WQ Output Interval=15MIN
WQ Output Selected Increments= 0
WQ Output face flow=0
WQ Output face velocity=0
WQ Output face area=0
WQ Output face dispersion=0
WQ Output cell volume=0
WQ Output cell surface area=0
WQ Output cell continuity=0
WQ Output cumulative cell continuity=0
WQ Output face conc=0
WQ Output face dconc_dx=0
WQ Output face courant=0
WQ Output face peclet=0
WQ Output face adv mass=0
WQ Output face disp mass=0
WQ Output cell mass=0
WQ Output cell source sink temp=0
WQ Output nsm pathways=0
WQ Output nsm derived pathways=0
WQ Create Restart=0
WQ Fixed Restart=0
WQ System Summary=0
WQ Write To DSS=0
Sorting and Armoring Iterations= 10
XS Update Threshold= 0.02
Bed Roughness Predictor= 0
Hydraulics Update Threshold= 0.02
Energy Slope Method= 1
Volume Change Method= 1
Sediment Retention Method= 0
Sediment TS Multiplier= 1
Warm Up Method= 0
XS Weighting Method= 0
Number of US Weighted Cross Sections= 1
Number of DS Weighted Cross Sections= 1
Upstream XS Weight=0
Main XS Weight=1
Downstream XS Weight=0
Number of DS XS's Weighted with US Boundary= 1
Upstream Boundary Weight= 1
Weight of XSs Associated with US Boundary= 0
Number of US XS's Weighted with DS Boundary= 1
Downstream Boundary Weight= 0.5
Weight of XSs Associated with DS Boundary= 0.5
Percentile Method= 0
Sediment Output Level= 3
Mass or Volume Output= 0
Output Increment Type= 1
Profile and TS Output Increment= 1
Transport Output Increment 1
XS Output Flag= 0
XS Output Increment= 10
Read HDF5 Sediment Hotstart= 0
Sediment Hotstart Type= 0
Write Gradation File= 0
Read Gradation Hotstart= 0
Write HDF5 File= 1
Write Binary Output= 1
Write DSS Sediment File= 0
DSS Sediment Output Type= 1
SV Curve= 0
Specific Gage Flag= 0
Subcell Erosion Methods= 0
Subcell Deposition Methods= 0
Advection Scheme= 1
Matrix Solver= 0
Implicit Weighting Factor= 1
Maximum Outer Loop Convergence Iterations= 5
Convergence Maximum Absolute= 0.001
Convergence RMSE= 0.0001
Grain Fractions Max Abs Error= 0.001
Max Subgrid Regions= 1
Max Subgrid Length Scale= 3.402823E+38
Initial Layer Thickness= 3.402823E+38
Min Layer Thickness= 3.402823E+38
Max Layer Thickness= 3.402823E+38
Number of Layers= 5

--- FALLRN.f01 (steady flow) ---

Flow Title=Flow
Program Version=6.20
Number of Profiles= 1
Profile Names=P100yr
River Rch & RM=FALLRN,Main            ,4914
     375
River Rch & RM=FALLRN,Main            ,1919
     537
Boundary for River Rch & Prof#=FALLRN,Main            , 1
Up Type= 0
Dn Type= 3
Dn Slope=0.0843
DSS Import GetInterval= 0
DSS Import GetPeak= 0
DSS Import FillOption= 0

--- FALLRN.g01 (geometry) ---

Geom Title=Geometry
Program Version=6.20

River Reach=FALLRN          ,Main
Reach XY= 30
2316042.38699999651868.7329999952316034.11745091651802.497277841
  2316073.089032651739.4550143112316041.61329736651626.395476207
2316064.96286164651490.9723913412316139.59225045651419.581384103
2316191.73549601651104.3890840262316295.51199998650935.921000004
2316259.15575207650593.1474940922316273.95693192650485.332977295
2316364.47994957650195.8850869632316380.61142425650026.002678859
2316433.27200003649960.6600000112316436.58308479649795.091186455
2316470.51200004649741.1289999932316356.18899998649600.765000016
2316455.66800003649463.0040000082316418.68900003649339.046000004
2316422.85600001649195.2960000042316375.00578807649058.663663998
2316535.23395212648891.8890246282316644.43804336 648688.75056344
2316669.32099999648536.3050759882316840.36773287648492.726910964
2316790.74217811648383.2696335762316796.28910536648275.011268809
2316868.49395934648031.8247782532316861.95546039647780.373418037
2316934.44648592647749.4966735222316870.40600003647610.229000002

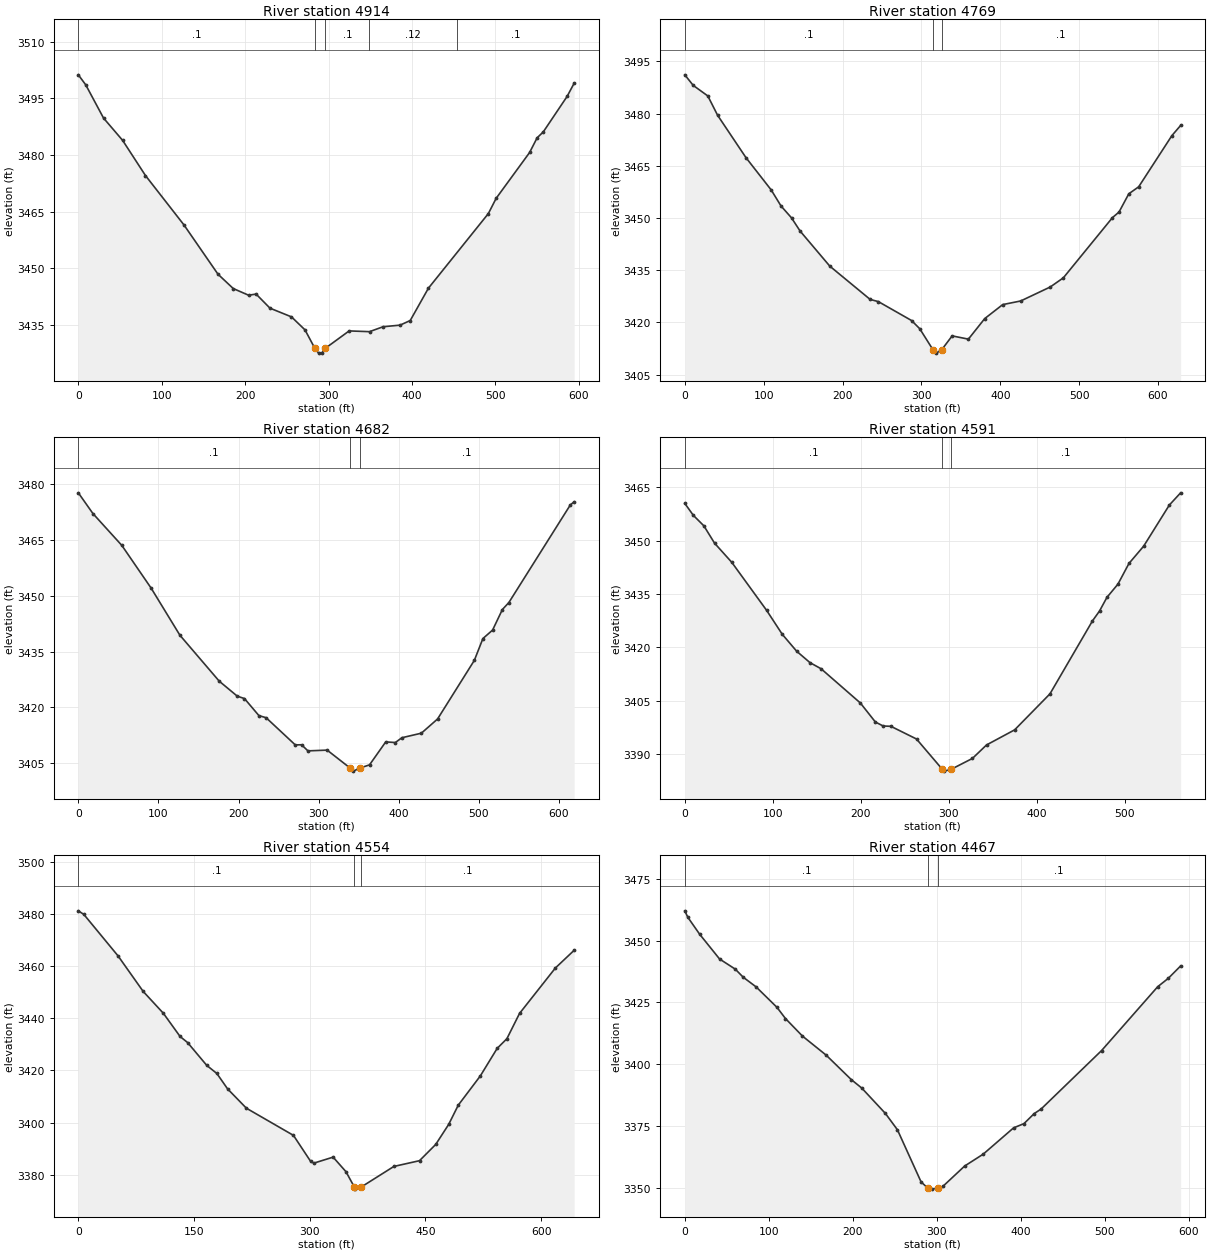
Type RM Length L Ch R = 1 ,4914    ,145.7,144.9,142.8
XS GIS Cut Line= 4
  2316306.575577651966.8318597882316106.64949324651856.029451926
2315934.02255346651824.7157279662315764.60727767651911.430655857
#Sta/Elev= 30
       0 3501.25     8.9 3498.59    30.2 3489.79    53.1 3483.87    80.5 3474.54
   126.6 3461.46   167.4 3448.39   185.7 3444.59     204 3442.83   213.1 3443.12
   229.7 3439.39   255.5 3437.08   271.7 3433.63  283.563428.708     288 3427.47
   292.1 3427.58   296.1 3428.76   324.6 3433.36     349 3433.16   365.2 3434.46
   385.6 3434.89   397.8 3436.11   419.6 3444.68   491.5 3464.48   500.8 3468.51
   540.9 3480.66   549.9 3484.55   557.3 3486.12   585.8 3495.51   594.3 3499.03
#Mann= 5, -1 ,  0
       0     0.1       0  283.56   0.045       0   296.1     0.1       0
  348.58    0.12       0  454.02     0.1       0
Bank Sta=283.56,296.1
XS Rating Curve= 0 ,0
Exp/Cntr(USF)=0,0
Exp/Cntr=0.3,0.1

Type RM Length L Ch R = 1 ,4769    ,85.8,86.4,86.7
XS GIS Cut Line= 4
2316323.38490529651908.0740660812316095.38709572651714.677398286
2316049.63267443651723.9258772362315776.85301452651799.546113321
#Sta/Elev= 30
       0 3491.13    10.7 3488.09    29.2 3485.06    41.6 3479.51    77.6 3467.33
   109.6 3458.05     122 3453.46   135.3 3450.05   146.2 3446.26   183.8 3436.19
     235 3426.62   245.5 3425.98   287.5 3420.56   297.9  3418.2  314.653412.173
   318.6 3411.19   325.5 3412.09     339 3416.14   359.6 3415.21   380.3 3421.11
   403.1 3425.13   425.9 3426.17   463.4 3430.19     480 3432.82   542.3 3450.12
   550.6 3451.72     563 3456.96   575.5 3458.96   617.6 3473.66   628.7 3476.59
#Mann= 3, -1 ,  0
       0     0.1       0  314.65   0.045       0   325.5     0.1       0
Bank Sta=314.65,325.5
XS Rating Curve= 0 ,0
Exp/Cntr(USF)=0,0
Exp/Cntr=0.3,0.1

Type RM Length L Ch R = 1 ,4682    ,89.6,91.8,91.7
XS GIS Cut Line= 3
2316360.37434893651751.450178334 2316119.8365757651627.027936119
2315775.53430028651678.067621043
#Sta/Elev= 30
       0 3477.62    18.2 3472.06    54.3  3463.5    90.9 3452.02   126.8 3439.38
   175.9 3427.04   198.4 3423.02   207.4 3422.37   225.4  3417.8   234.4 3417.23
   270.8 3409.93   278.6 3409.97   286.6 3408.33   310.6 3408.53   339.3 3403.71
   343.3 3402.89   351.3  3403.7   363.5 3404.58   383.7 3410.74   395.7 3410.57
   403.9 3411.86   428.2 3413.08   448.4 3416.89   494.3 3432.63     505 3438.49
   517.1 3440.77   529.3 3446.28   537.4 3448.16   614.2  3474.4   618.9  3475.2
#Mann= 3, -1 ,  0
       0     0.1       0   339.3   0.045       0   351.3     0.1       0
Bank Sta=339.3,351.3
XS Rating Curve= 0 ,0
Exp/Cntr(USF)=0,0
Exp/Cntr=0.3,0.1

Type RM Length L Ch R = 1 ,4591    ,35.2,37,37.8
XS GIS Cut Line= 4
2316332.58465437651669.6008288982316075.56351565 651550.37657108
2315895.82845361651554.5703891942315799.96975386 651583.32799912
#Sta/Elev= 30
       0 3460.45     9.7 3457.09    21.7 3454.13    33.8 3449.27    53.4 3443.87
      93 3430.36   110.7 3423.65   127.1 3418.88   142.2 3415.68   154.8 3413.96
   199.4 3404.34   216.5 3398.98   225.3 3397.87   234.1 3397.78   263.2 3394.21
   292.53385.697   294.7 3385.18   302.7 3385.71   326.7 3388.75   342.7 3392.53
   374.7 3396.79   414.8 3406.91   463.1 3427.43   471.1  3430.2   479.5 3434.03
     492 3437.75   504.5 3443.56   521.2 3448.42   550.4 3459.99   563.2 3463.42
#Mann= 3, -1 ,  0
       0     0.1       0   292.5   0.045       0   302.7     0.1       0
Bank Sta=292.5,302.7
XS Rating Curve= 0 ,0
Exp/Cntr(USF)=0,0
Exp/Cntr=0.3,0.1

Type RM Length L Ch R = 1 ,4554    ,85.5,87,87.4
XS GIS Cut Line= 4
2316397.64602726651649.2079994722316119.76492001651531.778968941
2315983.67961328651494.3996379392315793.09079656651554.912584227
#Sta/Elev= 30
       0 3481.13     7.2 3479.74    51.5 3463.85    84.1 3450.23   110.2 3441.88
   131.9 3432.97   141.6 3430.66   166.6 3421.86   179.6 3418.79   193.5 3412.89
   217.9 3405.48   278.9 3395.07   301.2 3385.09   305.4 3384.44   330.3 3386.73
   346.9 3381.18  357.953375.204   359.3 3374.47     366 3375.14   409.1 3383.17
   442.3 3385.37   463.3 3391.59   480.1 3399.26   492.6 3406.67   521.1 3417.83
     543 3428.42   555.6 3432.12     572 3441.81   618.5 3459.23   642.8 3466.01
#Mann= 3, -1 ,  0
       0     0.1       0  357.95   0.045       0     366     0.1       0
Bank Sta=357.95,366
XS Rating Curve= 0 ,0
Exp/Cntr(USF)=0,0
Exp/Cntr=0.3,0.1

Type RM Length L Ch R = 1 ,4467    ,66.4,65.5,64.1
XS GIS Cut Line= 3
2316359.23284903651603.0147507052316068.32832269651422.614003253
2315825.35314624 651471.87472396
#Sta/Elev= 30
       0 3462.03     3.6 3459.42    17.7 3452.56    41.4 3442.55    60.1 3438.45
    69.5 3435.19    84.9 3431.27   109.7 3423.01   119.8 3418.49   140.1 3411.37
   168.3 3403.67   198.2 3393.78   210.7 3390.35   238.8  3380.1   253.1  3373.5
   281.3 3352.39  289.143349.965   294.1  3349.5   301.2 3349.99   307.1 3350.58
   333.1 3358.83   355.2 3363.64   391.4 3374.28   403.7 3375.98   415.9 3380.04
   424.1 3381.88   496.1 3405.52   562.9 3431.34   575.4  3434.7   590.2 3439.74
#Mann= 3, -1 ,  0
       0     0.1       0  289.14   0.045       0   301.2     0.1       0
Bank Sta=289.14,301.2
XS Rating Curve= 0 ,0
Exp/Cntr(USF)=0,0
Exp/Cntr=0.3,0.1

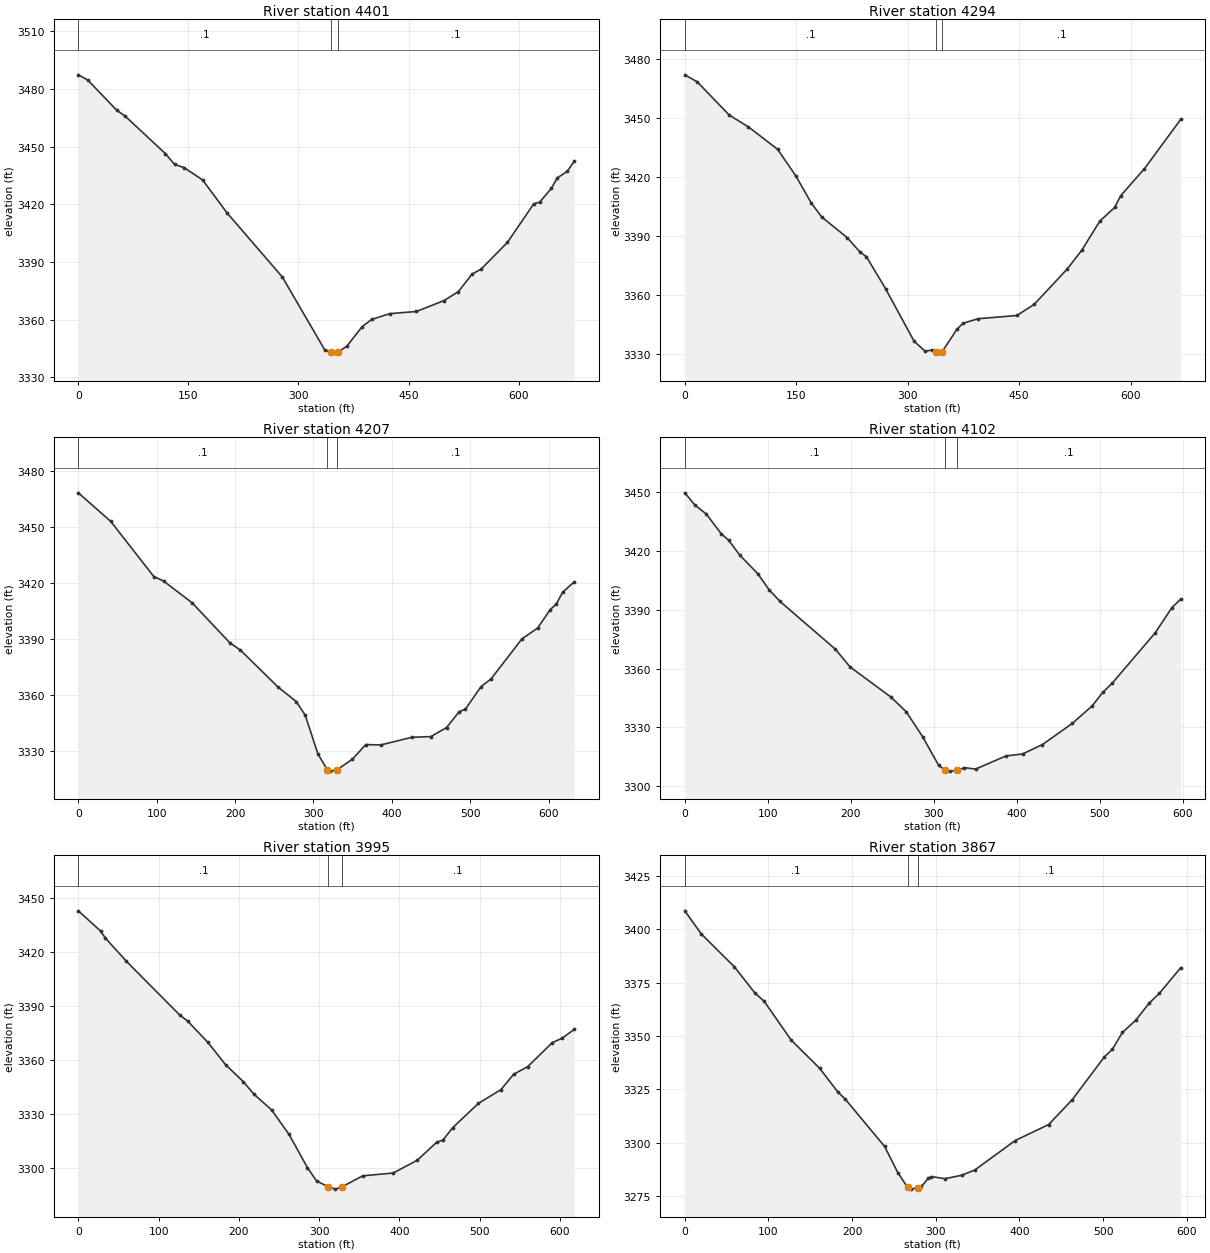
Type RM Length L Ch R = 1 ,4401    ,107.9,107.4,107
XS GIS Cut Line= 4
2316472.40692264651503.3856007542316301.04071555651444.923381166
2315970.20116323651345.0134370342315821.15165882651346.792386324
#Sta/Elev= 30
       0 3487.35    12.9 3484.63    52.3 3468.94    63.6 3465.94   118.6 3446.39
   131.1 3440.76   144.4    3439   169.3 3432.69   202.9 3415.42   278.1 3382.12
   335.6 3344.39   344.4    3343   349.1 3342.56  353.693343.014   365.8 3346.12
   386.9 3356.37   399.8 3360.09   424.3 3363.09   460.8 3364.23   498.4 3369.91
     518  3374.6   536.6  3383.7   548.7 3386.19   584.7 3400.13   620.7 3420.26
   628.7  3421.1   644.7 3428.31   652.7 3433.72   666.2 3437.08   675.7 3442.34
#Mann= 3, -1 ,  0
       0     0.1       0   344.4   0.045       0  353.69     0.1       0
Bank Sta=344.4,353.69
XS Rating Curve= 0 ,0
Exp/Cntr=0.3,0.1

Type RM Length L Ch R = 1 ,4294    ,89,86.5,85
XS GIS Cut Line= 4
2316463.74545918651411.2973511992316180.16347241651300.127886901
 2316104.2753351651282.820066113 2315819.3619775651278.160268208
#Sta/Elev= 30
       0 3472.19    16.7 3468.63    59.9 3451.69    85.5 3445.75   124.8 3434.36
   149.5 3420.76   170.2 3407.02   184.3  3399.9   218.7 3389.36   235.8  3382.1
   244.4 3379.74   270.2 3363.48   308.7  3336.7   323.8 3331.53   333.3 3332.39
  338.763331.272   341.5 3330.67  346.413331.368   366.1  3342.7   374.3 3345.79
   394.5 3348.15   447.1 3349.81   470.5 3355.54   515.1  3373.6   534.6 3383.13
   558.6  3397.8   578.6 3404.74   586.6 3410.68   618.6 3424.41   667.4 3449.48
#Mann= 3, -1 ,  0
       0     0.1       0  338.76   0.045       0  346.41     0.1       0
Bank Sta=338.76,346.41
XS Rating Curve= 0 ,0
Exp/Cntr(USF)=0,0
Exp/Cntr=0.3,0.1

Type RM Length L Ch R = 1 ,4207    ,101.5,105,107.3
XS GIS Cut Line= 4
 2316482.9726818651330.3717652172316425.51192548651312.007433003
2316220.50625767651219.3226861562315873.45937672651205.804813816
#Sta/Elev= 30
       0 3468.36    41.4 3453.05    96.3 3423.55   108.8 3421.14   145.1 3409.53
   193.5    3388   206.7 3384.22   254.9 3364.39   278.1 3356.61   289.6 3349.25
   305.7 3328.53   317.7 3320.19   321.7 3319.41   330.1 3320.15   349.7 3325.79
   366.7 3333.63   385.7 3333.41   425.7 3337.53   449.8  3337.9   469.8 3342.75
   485.8 3351.17   493.8 3352.56   513.8 3364.63   526.6 3368.79   565.9 3390.14
   585.9 3395.97   601.9 3405.74   609.9 3408.94   617.9 3415.14   632.6 3420.66
#Mann= 3, -1 ,  0
       0     0.1       0   317.7   0.045       0   330.1     0.1       0
Bank Sta=317.7,330.1
XS Rating Curve= 0 ,0
Exp/Cntr=0.3,0.1

Type RM Length L Ch R = 1 ,4102    ,106.2,107.5,108.3
XS GIS Cut Line= 3
2316479.56276834651254.1775362872316158.61891899651098.636136767
2315917.52156904651097.559353766
#Sta/Elev= 30
       0  3449.6    12.3 3443.33      26 3438.77    43.8 3428.79    52.7 3425.51
    66.5 3417.72    88.2 3408.26   101.6 3400.17   114.9 3394.19   181.6 3369.84
   199.3 3360.81   248.2 3345.55   266.8 3338.01   286.6 3325.32     306 3310.65
   314.1 3308.02   319.4 3307.69  328.483308.068   337.1 3309.47   350.5 3308.72
   387.1 3315.44   407.1 3316.41   431.1 3321.24   467.1 3332.01   491.1 3340.98
   503.9 3347.86   515.1 3352.47   567.1 3378.22   587.1 3391.03   597.7 3395.37
#Mann= 3, -1 ,  0
       0     0.1       0   314.1   0.045       0  328.48     0.1       0
Bank Sta=314.1,328.48
XS Rating Curve= 0 ,0
Exp/Cntr(USF)=0,0
Exp/Cntr=0.3,0.1

Type RM Length L Ch R = 1 ,3995    ,132,127.4,124.2
XS GIS Cut Line= 4
2316526.53904494651163.5637200032316295.38234487651056.294924543
2316169.98361214650974.7102068682315956.95684933650985.286003604
#Sta/Elev= 30
       0 3442.83    27.7 3431.63    33.5 3427.83    59.9 3414.86   126.1 3385.16
   136.1 3381.75   161.4 3369.92   183.4 3357.54   205.5 3348.17   218.7 3341.22
   240.7 3332.49   262.3 3319.03   285.4  3300.5   296.8 3293.05   311.4 3289.88
   320.1 3288.56   328.8 3289.89   354.1 3295.91   392.3 3297.49   422.3 3304.59
   446.3 3314.49   454.3 3315.78   466.3  3322.6   498.4 3336.08   526.4 3343.68
   542.4 3352.27   559.7 3356.41   590.5 3369.78   602.5 3372.15   617.7 3377.08
#Mann= 3, -1 ,  0
       0     0.1       0   311.4   0.045       0   328.8     0.1       0
Bank Sta=311.4,328.8
XS Rating Curve= 0 ,0
Exp/Cntr(USF)=0,0
Exp/Cntr=0.3,0.1

Type RM Length L Ch R = 1 ,3867    ,134.8,135.3,135.4
XS GIS Cut Line= 3
2316554.38803053650995.8442749712316332.79990845650908.551984456
2315978.59465271650921.981567612
#Sta/Elev= 30
       0 3408.71    19.6 3397.92    59.3 3382.46    83.7 3370.26    94.6 3366.45
   127.3 3348.08   161.1 3334.97   182.6 3323.98   191.9 3320.41   238.8 3298.33
   254.8  3285.9   266.4 3279.08   270.8 3278.31   278.8 3279.07   282.8 3279.55
   290.8 3283.29   294.8 3284.18   310.8 3283.21   330.9 3284.79   346.9 3287.34
   394.9 3301.09   434.9 3308.58   463.1 3320.24   501.6 3340.33     511  3343.8
     523  3351.7     539 3357.47     555 3365.45   567.2 3370.06   592.6 3381.99
#Mann= 3, -1 ,  0
       0     0.1       0   266.4   0.045       0   278.8     0.1       0
Bank Sta=266.4,278.8
XS Rating Curve= 0 ,0
Exp/Cntr(USF)=0,0
Exp/Cntr=0.3,0.1

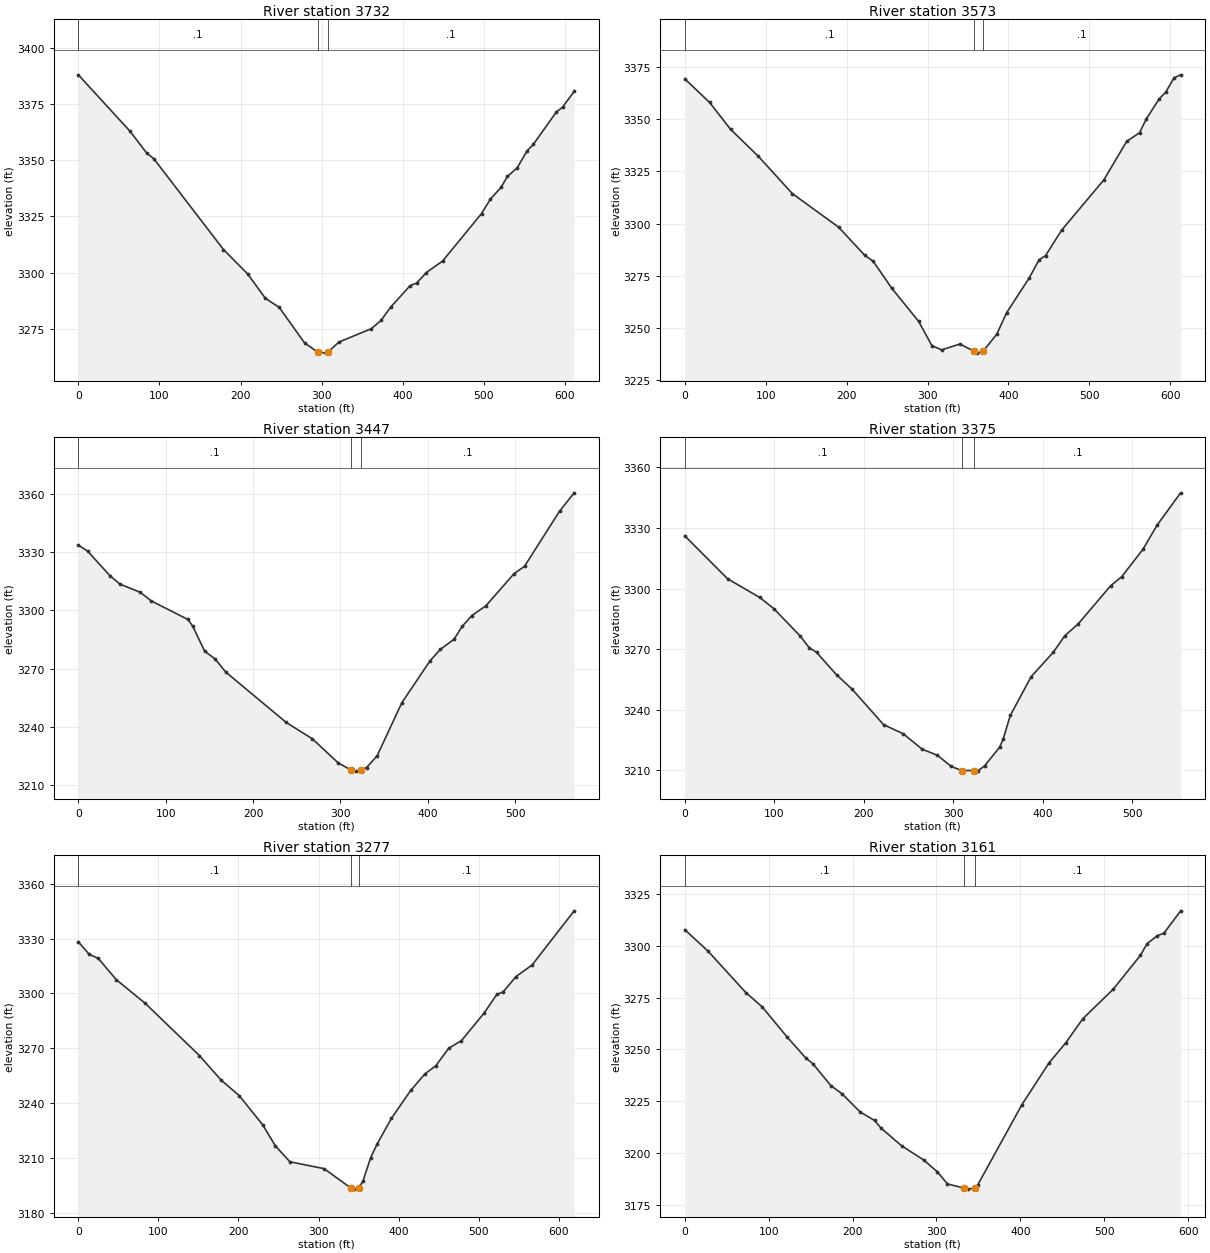
Type RM Length L Ch R = 1 ,3732    ,159.6,158.9,158
XS GIS Cut Line= 3
2316582.65651674650873.2820524242316334.04135854650775.078225594
2315989.90829017650774.071006858
#Sta/Elev= 30
       0 3387.97    63.7 3362.91    84.4 3353.13      93  3350.7     179 3310.27
   208.6 3299.51   230.6 3288.63   247.8 3284.52     279 3268.74     295 3264.74
   305.2 3264.22  308.093264.749   321.2 3269.12   361.2 3275.08   373.2 3278.74
   385.2 3284.69   409.2 3294.26   417.2 3295.37   429.2 3300.07   449.2 3305.18
   497.2 3326.29     508 3332.62   521.2 3337.93   529.2 3342.81   541.2 3346.62
   553.2 3354.09   561.2  3357.1   589.2 3371.34   597.2 3373.64   611.4 3380.62
#Mann= 3, -1 ,  0
       0     0.1       0     295   0.045       0  308.09     0.1       0
Bank Sta=295,308.09
XS Rating Curve= 0 ,0
Exp/Cntr(USF)=0,0
Exp/Cntr=0.3,0.1

Type RM Length L Ch R = 1 ,3573    ,127,126.6,125.6
XS GIS Cut Line= 3
2316604.67052769650729.2437636652316331.14769704650620.332207997
2316013.66891924650644.272165462
#Sta/Elev= 30
       0  3369.3    30.7    3358    56.5 3345.19    90.9 3332.25   132.8 3314.44
     190 3298.38   222.1    3285     233 3281.95     256 3269.03     289 3253.26
   305.4 3241.65   317.4 3239.64   340.1 3242.43   357.5 3238.97   361.4 3238.07
  368.543238.941   385.6 3247.12   397.7 3257.38   425.8 3274.11   437.8 3282.71
   445.8  3284.7   465.8 3296.95     518 3321.02   546.1 3339.38   562.1 3343.55
   570.2 3350.01   586.2  3359.7   594.2 3362.85   604.7  3369.8   612.8 3371.24
#Mann= 3, -1 ,  0
       0     0.1       0   357.5   0.045       0  368.54     0.1       0
Bank Sta=357.5,368.54
XS Rating Curve= 0 ,0
Exp/Cntr=0.3,0.1

Type RM Length L Ch R = 1 ,3447    ,68.3,71.3,73
XS GIS Cut Line= 4
2316574.28965796650604.861518919 2316303.7069663650501.285355048
2316237.86785437650511.7232630352316027.50386264650528.584499014
#Sta/Elev= 30
       0 3333.54    10.7 3330.45    36.5 3317.64    47.9 3313.43    70.8  3309.3
    83.6 3304.79   125.3 3295.31   130.8  3291.9   144.6 3278.92   156.5 3274.99
   168.7 3268.21   237.8 3242.31   267.8 3233.85   297.4 3221.45  312.33 3217.73
   317.6 3217.22  323.87 3217.77   329.8 3219.06   341.9 3225.07   370.1 3252.33
   402.2 3273.83   414.3 3279.89   429.9 3285.08   439.5 3291.86   450.4 3297.32
   466.4 3302.32   498.5  3318.8   510.6 3322.66   550.7 3351.03   567.4 3360.47
#Mann= 3, -1 ,  0
       0     0.1       0  312.33   0.045       0  323.87     0.1       0
Bank Sta=312.33,323.87
XS Rating Curve= 0 ,0
Exp/Cntr(USF)=0,0
Exp/Cntr=0.3,0.1

Type RM Length L Ch R = 1 ,3375    ,98,98.3,98.5
XS GIS Cut Line= 4
2316583.12173395650556.6865589792316347.06443024 650451.50456311
2316264.36408234650430.6287471362316054.00009061650439.460823125
#Sta/Elev= 30
       0 3326.07    47.9 3304.79    83.7 3295.58    99.6    3290   129.1  3276.4
     139 3270.73   147.3 3268.37   169.6 3257.28   187.1  3250.1   222.2 3232.58
   244.1 3228.09   265.5 3220.38   282.5  3217.4   297.8 3211.88  309.533209.864
   323.3 3209.86   327.4 3209.56   335.2  3212.2   351.9 3221.38   355.9 3225.38
   363.9 3237.15   387.2 3256.33     412 3268.44   424.8 3276.58     440 3282.57
     476 3301.32   488.5 3305.87   512.1 3319.36   528.1 3331.45   554.3 3347.38
#Mann= 3, -1 ,  0
       0     0.1       0  309.53   0.045       0   323.3     0.1       0
Bank Sta=309.53,323.3
XS Rating Curve= 0 ,0
Exp/Cntr(USF)=0,0
Exp/Cntr=0.3,0.1

Type RM Length L Ch R = 1 ,3277    ,116.4,115.8,114.1
XS GIS Cut Line= 4
2316626.26453856650491.4103882142316377.81725017650362.150650335
2316282.13147018650331.9340882332316043.75636916 650345.36367139
#Sta/Elev= 30
       0 3328.24    13.5 3321.42    24.9 3319.16    47.4 3307.52    83.3 3294.69
   151.2 3266.05   178.2 3252.67   200.8 3244.19   230.2  3228.2   245.8 3216.79
   264.2 3207.96     307 3204.18   340.5 3193.54   344.7    3193  350.073193.548
   355.5 3197.46     365 3210.13     373 3217.53     391 3231.73   415.1 3246.96
   432.7 3255.94   446.5 3260.51   462.5 3270.01   478.5 3274.22   506.6 3289.19
   522.6 3299.44   530.6 3300.89   546.6 3309.25   566.7 3315.57   619.2 3345.18
#Mann= 3, -1 ,  0
       0     0.1       0   340.5   0.045       0  350.07     0.1       0
Bank Sta=340.5,350.07
XS Rating Curve= 0 ,0
Exp/Cntr(USF)=0,0
Exp/Cntr=0.3,0.1

Type RM Length L Ch R = 1 ,3161    ,106.2,107.4,106.5
XS GIS Cut Line= 3
2316665.39140266650340.8484170422316426.46474665 650242.59525345
2316096.60478379650199.699905153
#Sta/Elev= 30
       0 3307.75    27.3 3297.58    72.8  3277.4    92.1 3270.57   122.4 3255.76
     144 3245.95   152.7 3243.07   174.3 3232.45   187.3 3228.61   208.9 3219.86
   226.2 3215.69   233.6 3212.14   258.3 3203.52   284.9 3196.59     301 3190.95
   313.1 3185.06     333 3183.07   337.3 3182.57  345.993183.118   349.4 3184.79
   401.8 3223.33   434.1 3243.45   454.3 3253.28   474.4 3264.79   510.7 3279.05
     543 3295.35   551.1 3301.08   563.2 3304.84   571.2  3306.1     591 3316.86
#Mann= 3, -1 ,  0
       0     0.1       0     333   0.045       0  345.99     0.1       0
Bank Sta=333,345.99
XS Rating Curve= 0 ,0
Exp/Cntr(USF)=0,0
Exp/Cntr=0.3,0.1

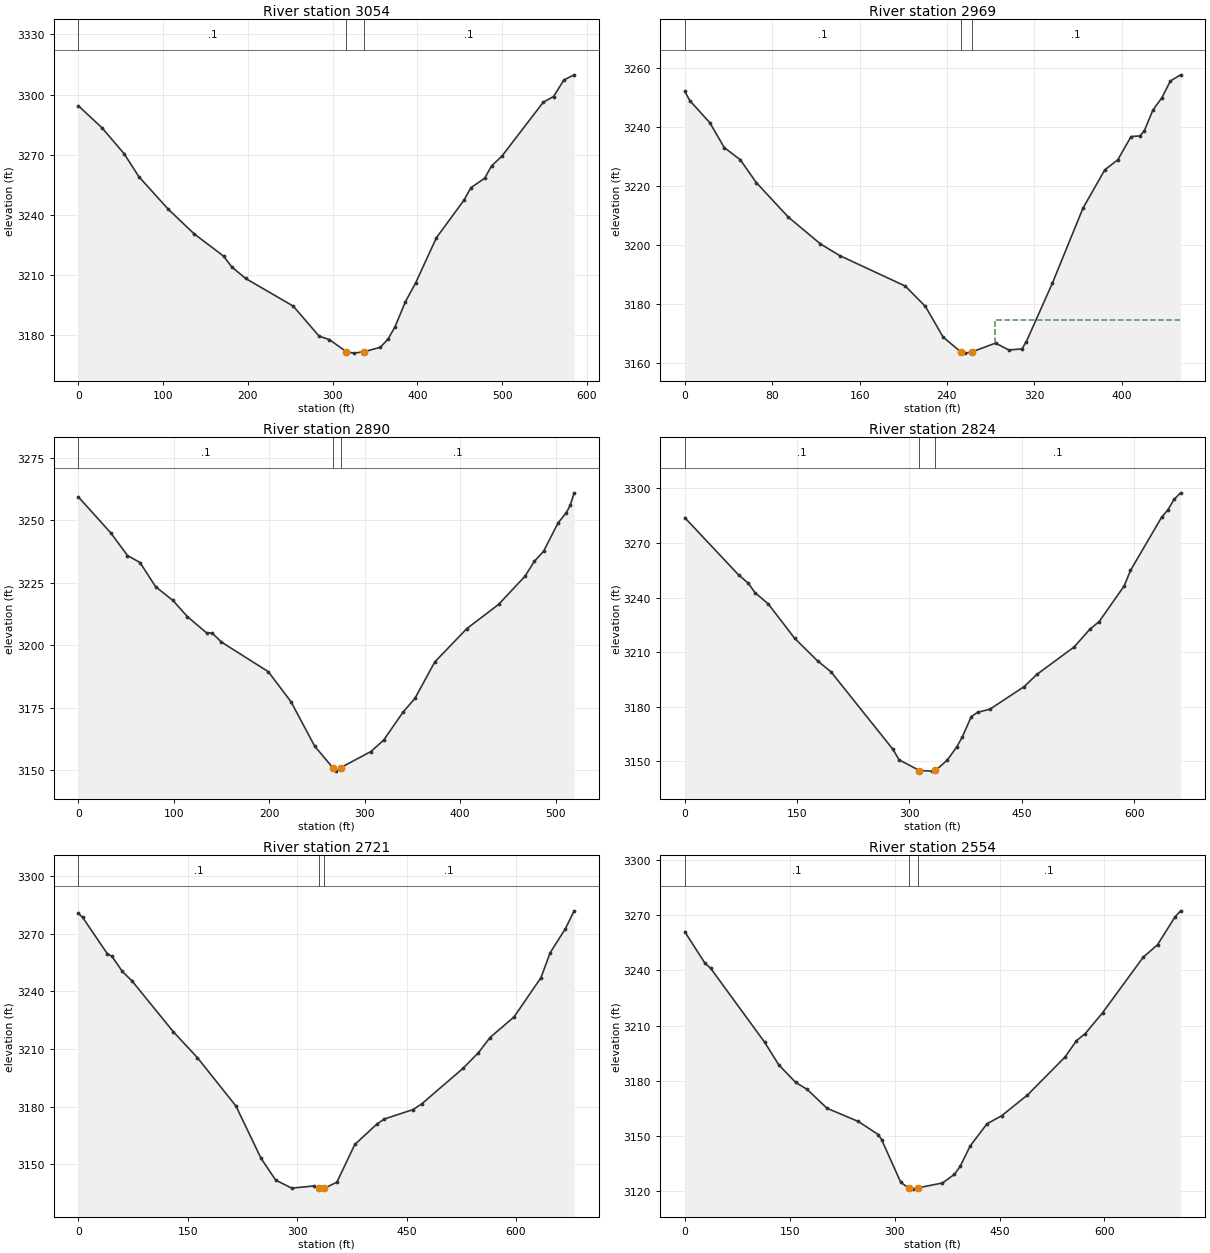
Type RM Length L Ch R = 1 ,3054    ,85.5,85.1,84.6
XS GIS Cut Line= 4
2316665.99500791650247.4568658222316407.18824197650138.415759711
2316281.18266402650114.5306938852316108.30993312650146.002159773
#Sta/Elev= 30
       0 3294.42      28 3283.39    54.1 3270.44    71.4 3259.04   106.1  3242.8
   136.5 3230.56   171.3 3219.43     181 3214.01   197.3 3208.28   253.5 3194.47
   283.9 3179.53   296.1 3177.76  315.973171.769   324.6 3171.03   336.8 3171.71
   356.3 3173.96   365.3 3178.08   373.5 3184.14   385.7 3196.61   397.9 3206.11
   422.3 3228.57   454.8 3247.31     463 3253.53   479.2 3258.24   487.4 3264.45
   499.6 3269.29   548.3 3296.18   560.5 3299.02   572.7  3307.3   584.8 3309.85
#Mann= 3, -1 ,  0
       0     0.1       0  315.97   0.045       0   336.8     0.1       0
Bank Sta=315.97,336.8
XS Rating Curve= 0 ,0
Exp/Cntr(USF)=0,0
Exp/Cntr=0.3,0.1

Type RM Length L Ch R = 1 ,2969    ,74.8,78.6,80.1
XS GIS Cut Line= 3
2316616.22831156650158.2402390812316422.49959809650049.392662955
2316190.82402322650048.893362147
#Sta/Elev= 30
       0 3251.93     4.6 3248.83      23 3241.31    36.1 3232.96    50.8 3228.82
    65.4 3221.12    94.8 3209.42   124.2 3200.36   141.8 3196.42   201.9 3186.09
   220.3 3179.21   236.5 3168.85   252.83163.801   256.5 3163.43  262.49 3163.81
   284.5 3166.82   296.6  3164.5   308.6 3164.86   312.6 3167.27   336.6 3187.18
   364.5 3212.45   384.5 3225.42   396.4 3228.83   408.5 3236.67   416.5 3236.89
   420.5 3238.46   428.5 3245.63   436.8 3249.84   444.5 3255.46   453.9 3257.55
#Mann= 3, -1 ,  0
       0     0.1       0   252.8   0.045       0  262.49     0.1       0
#XS Ineff= 2 , 0
                          284.34         3174.59
Permanent Ineff=
       F       F
Bank Sta=252.8,262.49
XS Rating Curve= 0 ,0
Exp/Cntr(USF)=0,0
Exp/Cntr=0.3,0.1

Type RM Length L Ch R = 1 ,2890    ,68.9,66.1,64.7
XS GIS Cut Line= 4
2316642.04842757650142.7320290552316445.83534234650002.452326022
2316384.54050831649970.0768917832316184.13965664650029.041235094
#Sta/Elev= 30
       0 3259.34      34 3244.92    51.5 3235.89    64.6 3233.09      81 3223.39
      99 3217.96   114.3 3211.44   134.3 3204.97   140.1 3204.92   149.8 3201.31
     199 3189.44   222.8 3177.41   247.6 3159.66  266.71 3150.99   270.2 3149.68
   274.7 3151.04   306.4  3157.5   319.8 3162.04   340.1 3173.25   352.6 3178.76
   373.4 3193.33   406.9 3206.64   440.2 3216.32     468 3227.65   477.6 3233.51
   487.3 3237.55   502.7 3249.01     511 3252.89   515.2  3255.9   519.4 3260.95
#Mann= 3, -1 ,  0
       0     0.1       0  266.71   0.045       0   274.7     0.1       0
Bank Sta=266.71,274.7
XS Rating Curve= 0 ,0
Exp/Cntr(USF)=0,0
Exp/Cntr=0.3,0.1

Type RM Length L Ch R = 1 ,2824    ,103.9,102.8,102.2
XS GIS Cut Line= 4
2316733.26702576650044.4261516182316488.37764607649931.214995759
2316375.16649021649919.9741717732316107.79546254649997.857023676
#Sta/Elev= 30
       0 3283.93    71.7 3252.54    84.9 3247.87    93.7 3242.74   111.4 3236.55
   146.6 3217.67   177.5 3205.13   195.1 3199.25     278 3156.56   286.1 3150.83
   313.33144.958   330.2 3144.63   334.7 3144.98   350.4 3150.67   363.3 3158.04
   370.6 3163.52   382.5 3174.58   390.8 3176.93   407.5  3178.7   453.3 3191.14
     470 3197.76     520 3212.93   540.8 3222.62   553.3 3226.86   586.7 3246.47
     595  3254.9   636.7 3284.24     645 3288.21   653.3 3294.05     662 3297.59
#Mann= 3, -1 ,  0
       0     0.1       0   313.3   0.045       0   334.7     0.1       0
Bank Sta=313.3,334.7
XS Rating Curve= 0 ,0
Exp/Cntr(USF)=0,0
Exp/Cntr=0.3,0.1

Type RM Length L Ch R = 1 ,2721    ,170.1,167.6,162.2
XS GIS Cut Line= 4
2316757.67559303649911.0345838942316501.22430205649811.580511909
2316374.47217521 649842.773134192316108.17623457649907.729173732
#Sta/Elev= 30
       0 3280.49     5.9 3278.45    39.7 3259.49    45.9 3258.24    60.4 3250.28
    73.7 3245.32   130.3 3218.89   163.3 3205.42   216.1 3180.26   250.4 3153.13
   270.6 3141.71   292.6 3137.58   323.5 3138.74  329.44 3137.43   333.8 3137.06
   336.8 3137.42   354.4 3140.67   379.1 3160.34   409.5 3170.96   419.4 3173.52
   459.1 3178.48   470.8 3181.43   527.4  3199.9   548.5 3208.07   564.4 3215.92
   597.4 3226.68   634.2 3247.07   646.8 3260.04   667.7 3272.55   679.7 3281.83
#Mann= 3, -1 ,  0
       0     0.1       0  329.44   0.045       0   336.8     0.1       0
Bank Sta=329.44,336.8
XS Rating Curve= 0 ,0
Exp/Cntr=0.3,0.1

Type RM Length L Ch R = 1 ,2554    ,128.7,133,141
XS GIS Cut Line= 4
2316748.59641338649696.1049987252316474.59130168649648.449427583
2316365.76874875649742.8468902492316088.28758661649814.872759784
#Sta/Elev= 30
       0 3261.09    28.8 3243.98      37 3241.18   114.1 3200.97   134.4  3188.6
   158.5 3179.06     175 3175.25   203.3    3165   248.1 3157.78   276.5 3150.69
   281.3 3147.96   308.7  3124.7     320 3121.56   325.7 3120.95  332.72  3121.6
   368.3 3124.28   385.3 3128.92   393.8 3133.38   407.9 3144.39   432.1 3156.53
   452.8 3160.84   489.9 3172.18   543.7 3192.89   559.9 3201.75   572.6 3205.68
   597.4 3217.02   655.2 3247.13   675.9 3254.03   700.7 3269.07   708.9 3272.48
#Mann= 3, -1 ,  0
       0     0.1       0     320   0.045       0  332.72     0.1       0
Bank Sta=320,332.72
XS Rating Curve= 0 ,0
Exp/Cntr=0.3,0.1

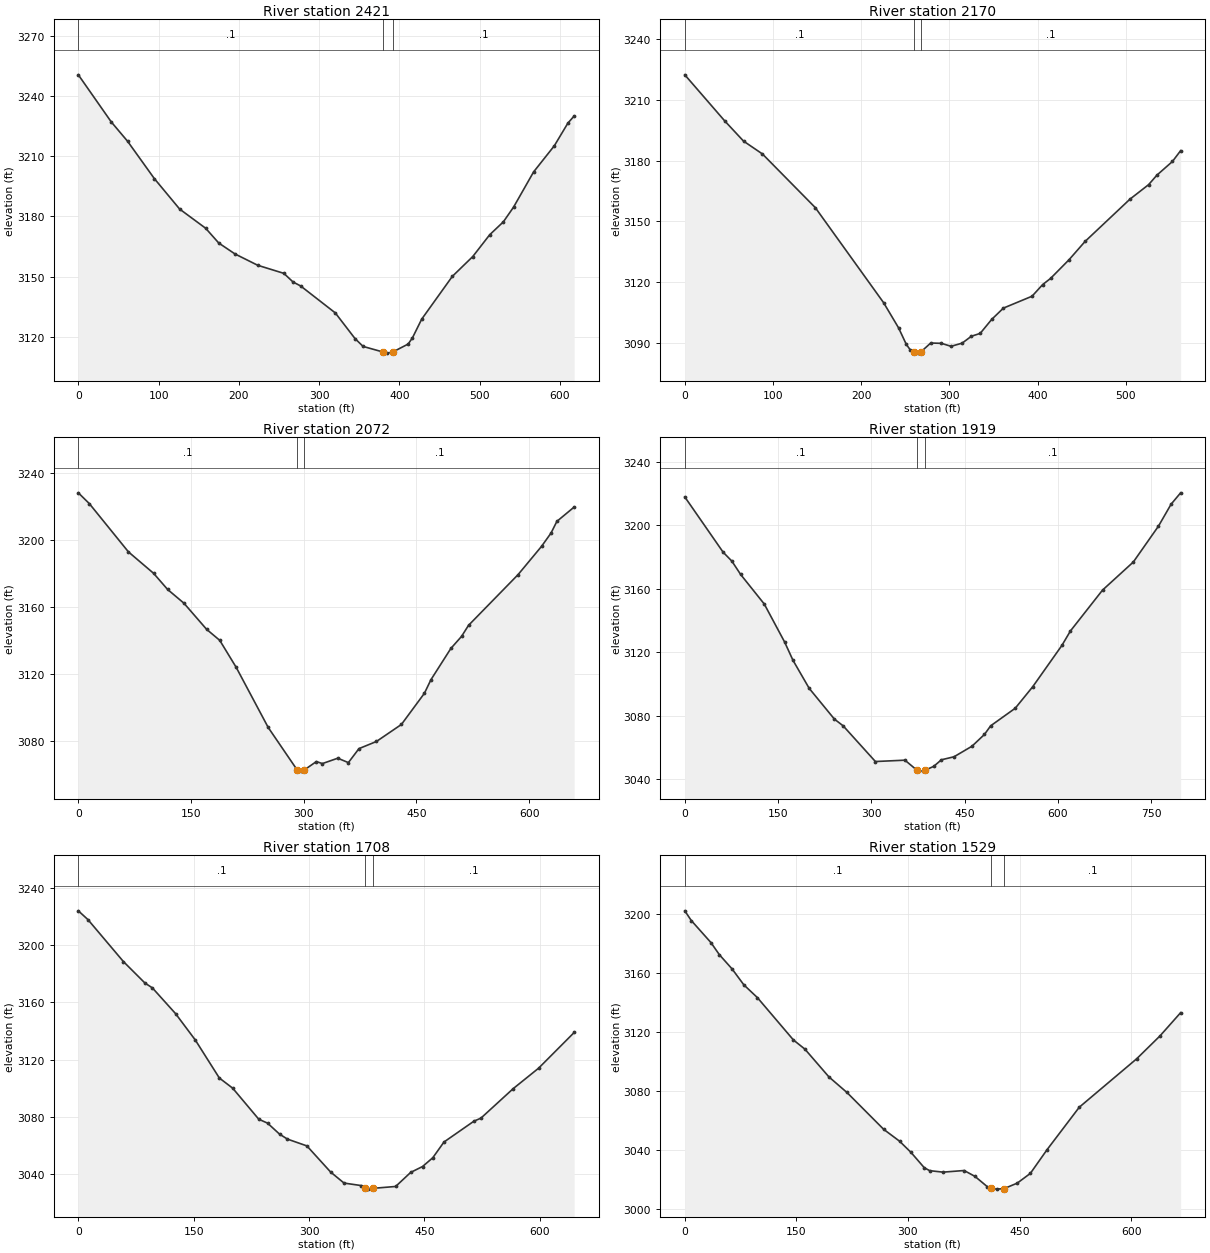
Type RM Length L Ch R = 1 ,2421    ,253.4,250.9,246.8
XS GIS Cut Line= 4
 2316728.5889029649673.7907183142316464.91525385649629.184273925
 2316337.0434466649576.6477949782316136.81007401649646.035597361
#Sta/Elev= 30
       0 3250.55      41 3227.08    61.3 3217.46    94.6 3198.87   126.2 3183.64
   158.6 3174.08   174.9 3166.72   195.1 3161.28   223.5 3155.62     256  3151.6
   267.4 3147.31   276.9 3145.32   320.1 3131.88   344.6 3119.11   354.7 3115.18
   379.93112.354     385 3111.84  391.473112.364   410.8 3116.36   416.2 3119.48
   427.7 3128.78   465.9 3150.12   491.3 3159.97   512.4 3170.84   529.4 3177.27
   542.1 3184.59   567.1 3202.17   592.9 3215.19   609.8 3226.48   617.6 3230.04
#Mann= 3, -1 ,  0
       0     0.1       0   379.9   0.045       0  391.47     0.1       0
Bank Sta=379.9,391.47
XS Rating Curve= 0 ,0
Exp/Cntr(USF)=0,0
Exp/Cntr=0.3,0.1

Type RM Length L Ch R = 1 ,2170    ,96.1,98.1,99.2
XS GIS Cut Line= 4
2316686.28623179649454.6139856762316454.78947205649365.242561956
2316337.10708513649433.0058253812316175.86060849649509.280546861
#Sta/Elev= 30
       0 3222.31    45.1 3199.65    66.6  3189.6      88 3183.26     148 3156.76
   225.5 3109.81   242.4 3097.44   251.2 3089.26   255.8 3086.48   260.4 3085.52
   264.7 3084.94   267.6 3085.51   278.9 3089.93     291 3089.78   301.9 3088.31
   314.5 3089.86     325 3093.27     335 3094.68   348.1 3101.61   361.3 3107.16
   393.8 3113.03   405.8 3118.76   414.8 3121.82   435.8 3131.06   453.9 3140.05
   504.9 3160.96     526  3168.1   535.4 3172.79     553 3179.53   562.3 3184.88
#Mann= 3, -1 ,  0
       0     0.1       0   260.4   0.045       0   267.6     0.1       0
Bank Sta=260.4,267.6
XS Rating Curve= 0 ,0
Exp/Cntr(USF)=0,0
Exp/Cntr=0.3,0.1

Type RM Length L Ch R = 1 ,2072    ,156.6,152.6,150.3
XS GIS Cut Line= 4
2316709.70077307 649378.646544932316482.60612222649283.387276517
2316386.66454086649288.9291565172316116.67973229649455.992716825
#Sta/Elev= 30
       0 3227.89    14.7 3221.43    66.7 3192.68   100.1 3179.94   118.8 3170.31
   140.5 3162.12   170.8  3146.5   188.2 3139.97   210.1 3123.87   252.7 3088.04
  291.243062.721   295.7 3062.01   300.8 3062.72   316.8 3067.71   324.8 3066.51
   345.3 3069.71   359.4 3067.09   373.5 3075.42   396.7 3079.67     430 3089.83
   460.6 3108.41   469.3 3116.51   495.8 3135.13     510  3142.3   519.3 3148.89
   585.2 3179.11   616.5 3195.99   629.1  3203.9   636.9 3210.87   659.9 3219.42
#Mann= 3, -1 ,  0
       0     0.1       0  291.24   0.045       0   300.8     0.1       0
Bank Sta=291.24,300.8
XS Rating Curve= 0 ,0
Exp/Cntr=0.3,0.1

Type RM Length L Ch R = 1 ,1919    ,199.3,210.7,214.1
XS GIS Cut Line= 4
2316716.47563835649264.3606577562316456.12638188649102.651689576
2316264.10012973649225.7338192032316103.34801935649433.271239904
#Sta/Elev= 30
       0 3217.84    61.6 3183.03    75.7 3177.38    89.8 3168.97   127.8 3150.34
   160.5 3126.39   173.9 3114.91     200 3097.21   240.5 3077.84   254.6 3073.59
   306.4 3051.11   353.9 3051.96   372.9 3045.75   382.4 3045.06  386.753045.735
   400.1 3048.04   412.5  3052.2   432.8  3054.1   461.7 3060.76   481.7 3068.17
   491.7 3073.61   531.2 3084.68   559.2 3098.17   606.3 3124.31   619.9 3133.36
   671.6 3159.15   721.1 3176.85   761.5 3199.45   781.8 3213.27   797.1 3220.43
#Mann= 3, -1 ,  0
       0     0.1       0   372.9   0.045       0  386.75     0.1       0
Bank Sta=372.9,386.75
XS Rating Curve= 0 ,0
Exp/Cntr(USF)=0,0
Exp/Cntr=0.3,0.1

Type RM Length L Ch R = 1 ,1708    ,177.2,178.9,177.5
XS GIS Cut Line= 3
2316770.29287662649212.5640213722316511.81546559649010.263129076
2316226.40894416648873.086260691
#Sta/Elev= 30
       0 3224.17    12.5 3218.02    58.6 3188.65    86.6 3173.62    96.4 3170.16
   126.4 3152.22   152.1 3133.73   183.4 3107.09   200.8 3099.95   234.7 3078.22
   246.1 3075.49   261.7  3067.8   271.9 3064.32   297.3 3059.53   328.2 3041.21
   345.6 3033.51   367.7 3031.78  373.19 3029.79   376.7 3029.27   382.7 3029.79
   412.7 3031.13   432.3 3040.99   447.7  3045.1     461 3051.23   475.6 3062.27
   514.6 3076.88   523.6 3078.97   565.6 3099.64   598.6 3113.94   644.9 3138.96
#Mann= 3, -1 ,  0
       0     0.1       0  373.19   0.045       0   382.7     0.1       0
Bank Sta=373.19,382.7
XS Rating Curve= 0 ,0
Exp/Cntr(USF)=0,0
Exp/Cntr=0.3,0.1

Type RM Length L Ch R = 1 ,1529    ,174.2,174.8,173.2
XS GIS Cut Line= 3
2316868.96754242649104.6784277232316662.31151818648897.320823994
2316327.34273952648731.612293036
#Sta/Elev= 30
       0    3202     8.7 3195.44    35.1 3180.51    46.5 3172.26    63.5 3162.67
    79.4 3151.83    97.5 3143.24   146.1 3114.45   161.4 3108.32   193.8 3089.44
     218 3078.91   267.4 3053.93   288.7 3045.92   304.1  3038.3   321.9 3027.95
   329.2 3025.95   347.2 3024.95   375.5 3026.05     390 3022.09   406.7 3015.07
  411.77 3013.91   419.9 3013.44   429.6 3013.86   446.9 3017.51   464.5  3024.1
     487  3040.2   530.3 3068.95   607.5 3101.79   638.8 3117.27   666.5 3132.99
#Mann= 3, -1 ,  0
       0     0.1       0  411.77   0.045       0   429.6     0.1       0
Bank Sta=411.77,429.6
XS Rating Curve= 0 ,0
Exp/Cntr(USF)=0,0
Exp/Cntr=0.3,0.1