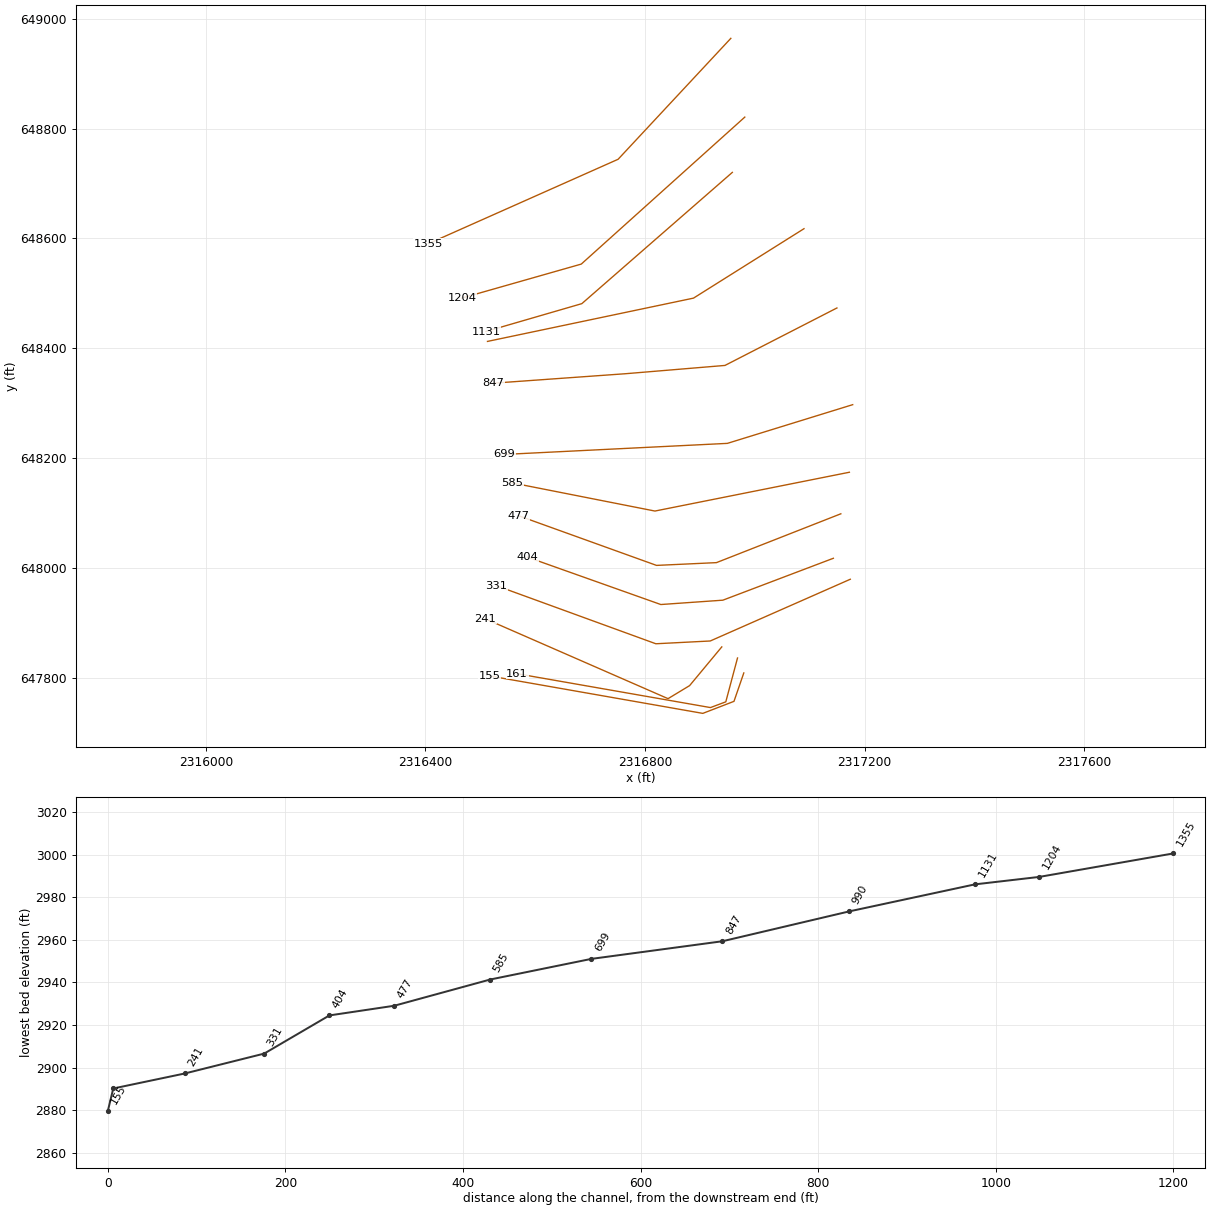
HEC-RAS study FALLRN.prj: FALLRN

--- FALLRN.g01 (geometry) --- (continued)

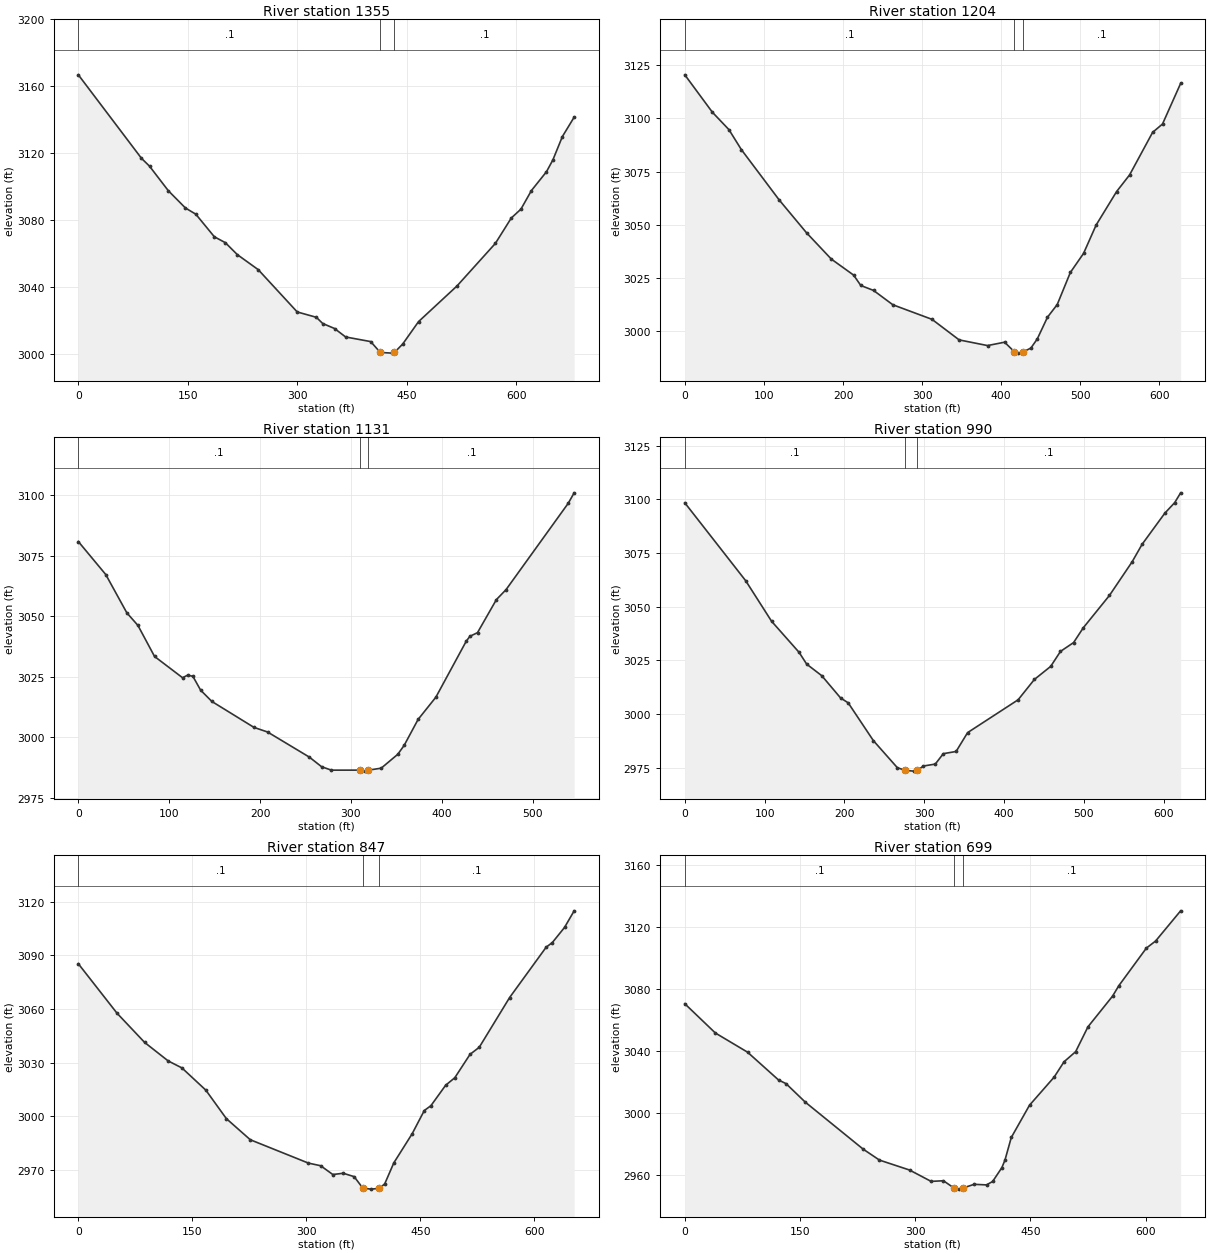
Type RM Length L Ch R = 1 ,1355    ,151.9,151.2,147.9
XS GIS Cut Line= 3
2316956.20998106648964.4847806692316750.88844158648744.206042948
2316405.51313675648590.554824661
#Sta/Elev= 30
       0 3166.92    86.5    3117    97.5 3112.31   123.2 3097.67   146.7 3087.31
   160.9 3083.61   186.3  3070.1   201.4 3066.57   217.8 3059.42   246.4 3050.45
   299.8 3025.16     326 3021.97   334.7 3018.26   350.9 3015.27   366.1 3010.21
   400.4 3007.45   413.6 3000.96   429.7 3000.55   432.93000.967   444.2 3005.94
     466  3019.4   518.6 3040.68   571.2 3066.15     593 3081.33   606.2 3086.62
   620.6 3097.75   641.2 3108.99     650  3116.1     663 3130.04   679.1 3141.61
#Mann= 3, -1 ,  0
       0     0.1       0   413.6   0.045       0   432.9     0.1       0
Bank Sta=413.6,432.9
XS Rating Curve= 0 ,0
Exp/Cntr(USF)=0,0
Exp/Cntr=0.3,0.1

Type RM Length L Ch R = 1 ,1204    ,68.5,72.3,73.7
XS GIS Cut Line= 3
2316981.65066491648821.0058804552316683.79810975648553.282981253
2316466.10530826648491.310951223
#Sta/Elev= 30
       0 3120.55    34.9 3102.92    55.8 3094.74    71.5 3085.34   119.4  3061.6
   153.9 3046.17   185.2  3033.8   213.4 3026.25   222.5 3021.36   238.6 3019.03
     263 3012.28   312.5 3005.42   346.8 2995.74   382.7 2993.07   404.3 2994.66
   416.7 2990.11   420.9 2989.51  427.642990.095   437.5 2991.89   445.6  2996.2
   458.5 3006.43   470.8 3012.37   487.4 3027.49   504.1 3036.47     520 3049.83
   545.9  3065.6   562.3 3073.43   591.4 3093.46   603.9 3097.39   626.8  3116.5
#Mann= 3, -1 ,  0
       0     0.1       0   416.7   0.045       0  427.64     0.1       0
Bank Sta=416.7,427.64
XS Rating Curve= 0 ,0
Exp/Cntr(USF)=0,0
Exp/Cntr=0.3,0.1

Type RM Length L Ch R = 1 ,1131    ,146.1,141.5,134.1
XS GIS Cut Line= 3
2316958.93941371648720.3092714812316684.82327018648481.244044659
2316510.01805733648430.465152496
#Sta/Elev= 30
       0  3080.9    30.2 3067.26    53.4 3051.43    65.6 3046.23    83.9 3033.41
   114.7 3024.62   120.4 3025.68   126.1  3025.2   134.6 3019.49     147 3014.81
   193.4 3004.08   208.3 3002.19   254.3 2991.81   267.8 2987.83   278.6 2986.42
  310.09 2986.43   315.1 2986.02   319.32986.423   333.4 2987.24   351.6 2992.96
   358.6 2996.62     374 3007.38   393.6 3016.59   426.9 3039.64     431 3041.73
   439.4 3043.24   460.2  3056.9   470.8 3061.01   539.3 3096.72   545.8 3101.03
#Mann= 3, -1 ,  0
       0     0.1       0  310.09   0.045       0   319.3     0.1       0
Bank Sta=310.09,319.3
XS Rating Curve= 0 ,0
Exp/Cntr(USF)=0,0
Exp/Cntr=0.3,0.1

Type RM Length L Ch R = 1 ,990     ,139.9,142.9,141.7
XS GIS Cut Line= 3
2317089.46501992648617.7497305532316888.22271633648491.293418158
2316512.93301503648412.428191072
#Sta/Elev= 30
       0  3098.4    76.3 3062.08   108.7  3043.2   143.2  3028.7   152.7 3023.21
   171.6 3017.82   195.2 3007.43   204.7 3005.17   236.3 2987.54   266.3 2974.94
   276.4 2973.68   286.8 2973.34  291.362973.686     299 2975.73   313.8 2976.62
   323.9 2981.48   339.9  2982.5   354.3 2991.28   417.6 3006.59     438 3016.07
   458.4 3022.15   470.7 3029.15   487.1 3033.26   499.3 3040.17     532 3055.21
   560.4 3070.87   572.9 3079.03   601.5 3093.61   613.8 3098.49   621.2 3103.05
#Mann= 3, -1 ,  0
       0     0.1       0   276.4   0.045       0  291.36     0.1       0
Bank Sta=276.4,291.36
XS Rating Curve= 0 ,0
Exp/Cntr(USF)=0,0
Exp/Cntr=0.3,0.1

Type RM Length L Ch R = 1 ,847     ,145.8,147.5,147.6
XS GIS Cut Line= 4
2317149.45861182648473.3594199462316945.52463996648368.682070028
2316764.22526735648353.5737889782316523.46937439648336.340541499
#Sta/Elev= 30
       0 3085.24    50.9 3057.61    87.2  3041.3   118.3 3030.92   136.3 3027.05
   167.8 3014.61   194.8  2998.7   226.3  2986.9   302.8 2973.85   318.9 2972.38
   334.9 2967.47   348.6 2968.18     363 2966.28   374.5  2959.8   385.6 2959.31
  396.222959.769   403.2 2962.25   415.2    2974   439.3 2990.24   455.3 3003.24
     464 3005.93   483.4 3017.36   495.4 3021.53   515.5 3034.63   527.6 3038.56
   567.6 3066.38   615.7 3094.51   623.8 3097.09   639.8 3105.51   652.5 3114.81
#Mann= 3, -1 ,  0
       0     0.1       0   374.5   0.045       0  396.22     0.1       0
Bank Sta=374.5,396.22
XS Rating Curve= 0 ,0
Exp/Cntr(USF)=0,0
Exp/Cntr=0.3,0.1

Type RM Length L Ch R = 1 ,699     ,112.4,114,115.6
XS GIS Cut Line= 3
2317178.19796189648297.2216834082316949.89504823648226.716371836
2316543.65015775648206.571997102
#Sta/Elev= 30
       0 3070.39    39.8 3051.55    81.7 3039.21   122.1  3021.3   131.9 3018.93
     157    3007   232.4 2976.74   253.5 2969.73   292.7 2963.33   320.8 2956.02
   336.8 2956.44  350.352951.821   356.8 2951.04   362.4 2951.78   376.8 2954.14
   392.9 2953.76   400.9 2955.97   412.9 2964.86   416.9 2969.67   425.2 2984.31
   448.9 3005.05     481 3023.16   493.9 3033.04     509 3039.53     525 3055.51
   557.1  3075.3   565.1 3081.91   601.1 3106.21   613.1 3110.75   645.7  3130.2
#Mann= 3, -1 ,  0
       0     0.1       0  350.35   0.045       0   362.4     0.1       0
Bank Sta=350.35,362.4
XS Rating Curve= 0 ,0
Exp/Cntr(USF)=0,0
Exp/Cntr=0.3,0.1

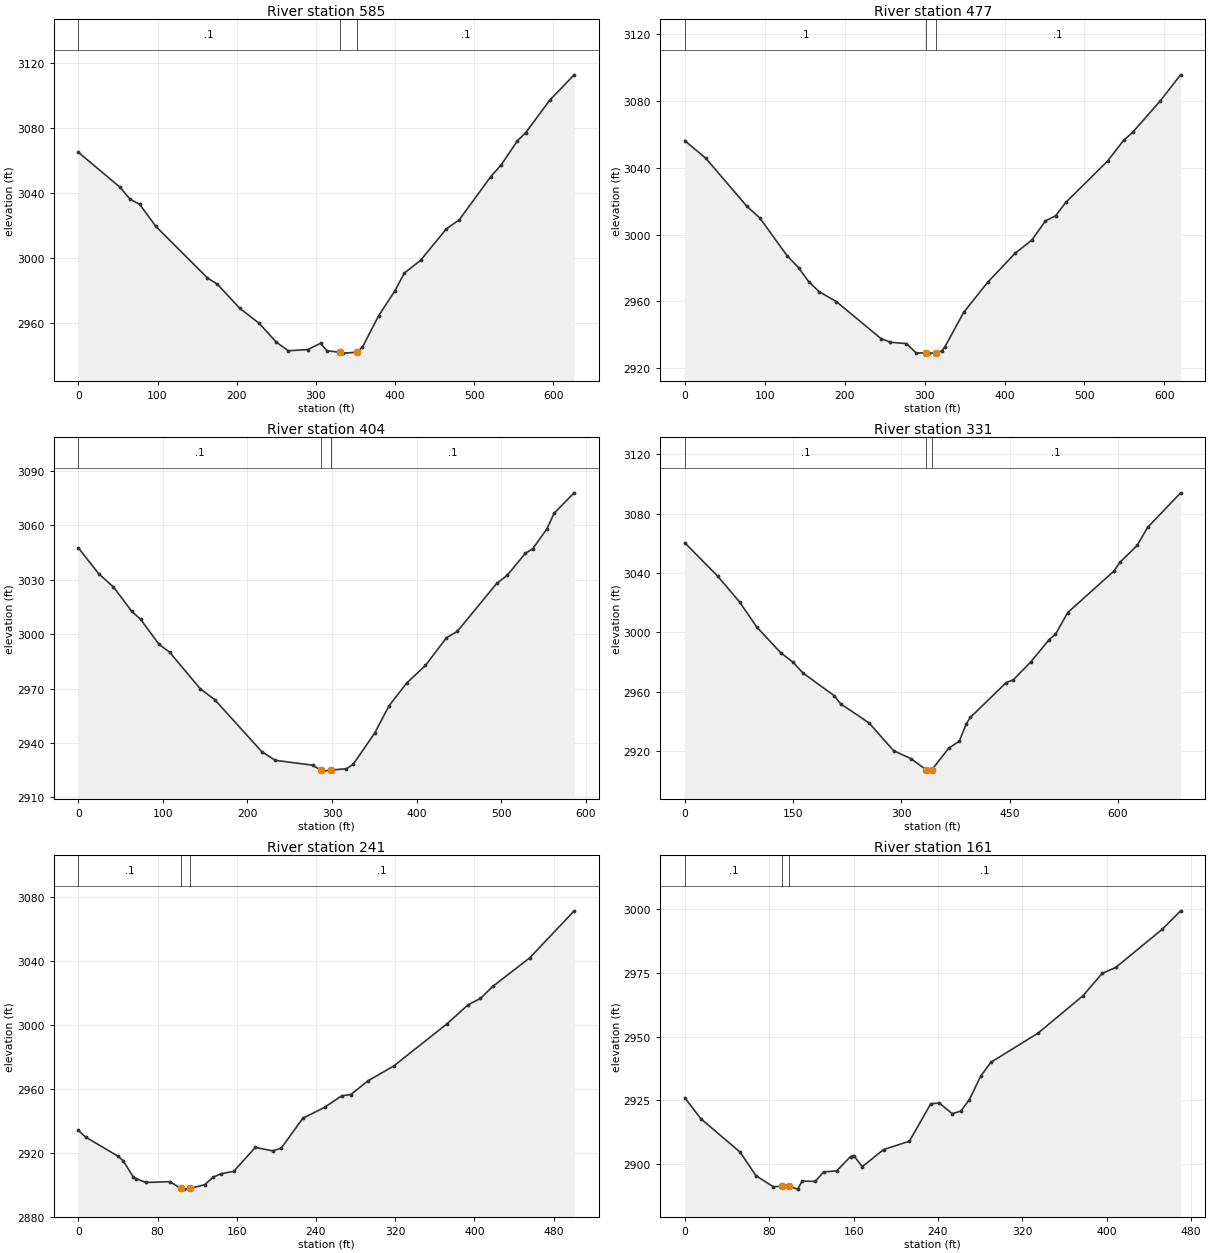
Type RM Length L Ch R = 1 ,585     ,107.8,108.1,107.3
XS GIS Cut Line= 3
2317172.15066919648174.1309076182316817.94359997648103.447802693
2316557.81434789648154.757548482
#Sta/Elev= 30
       0 3065.07      53 3043.39    65.2 3036.18    77.5    3033    97.9 3019.44
   163.1 2987.67   175.4 2983.91   203.9 2968.96   228.4 2959.73   250.1  2948.1
   265.1 2942.82   289.8 2943.53   305.9 2947.41     314 2942.84   330.6 2941.87
   334.4 2941.35  351.672941.887   358.9 2945.09   379.3 2964.34   399.7 2979.62
   411.8 2990.65   432.3 2998.53   464.9 3017.89   481.2 3023.48   520.8 3049.97
   534.2 3057.32   554.6 3072.14   565.1 3077.12   595.7 3097.27   626.3 3112.75
#Mann= 3, -1 ,  0
       0     0.1       0   330.6   0.045       0  351.67     0.1       0
Bank Sta=330.6,351.67
XS Rating Curve= 0 ,0
Exp/Cntr(USF)=0,0
Exp/Cntr=0.3,0.1

Type RM Length L Ch R = 1 ,477     ,72.4,73,72.7
XS GIS Cut Line= 4
2317156.61209981648098.4541967492316929.98788405648009.483208338
 2316820.8725209648004.4471146552316569.06783673648095.096800959
#Sta/Elev= 30
       0 3056.29    26.3 3045.76    77.8  3016.9    93.9 3009.95   127.8  2987.5
   142.3 2980.22   155.2 2971.74   168.1 2965.84   189.6  2959.9   245.3 2937.79
   257.3 2935.58   277.3 2934.73   289.3 2929.21   301.3 2929.11   305.3 2929.03
  313.842929.118   321.4 2930.29   325.4 2932.79   348.8 2953.38   378.9 2971.48
   413.2  2988.8   434.2 2996.79   451.2 3008.19     464 3011.35   476.7 3019.35
   528.9 3044.08     549  3056.5   560.1 3061.19   594.5 3079.95   620.3 3095.73
#Mann= 3, -1 ,  0
       0     0.1       0   301.3   0.045       0  313.84     0.1       0
Bank Sta=301.3,313.84
XS Rating Curve= 0 ,0
Exp/Cntr(USF)=0,0
Exp/Cntr=0.3,0.1

Type RM Length L Ch R = 1 ,404     ,73.9,73.5,73.1
XS GIS Cut Line= 4
2317142.94549813648017.4276906072316941.72087122647941.101107987
2316828.71787877647933.1710734292316585.86057043648019.410199247
#Sta/Elev= 30
       0 3047.53    24.4 3033.13    41.5    3026    62.9 3012.71    73.7 3008.13
    95.4 2994.33   107.8 2990.11   144.1  2969.9   161.3 2963.87   216.8 2935.28
   232.8 2930.45   276.9 2927.77  286.712925.019   288.9 2924.49   298.9 2925.05
     317 2925.82   324.8 2928.17   350.3  2945.4   367.3 2960.49   388.4 2973.13
   410.4 2982.74   435.2 2997.96     448 3001.49   494.6 3027.93   507.1 3032.41
   528.6 3044.61   537.1 3046.97     554 3058.01   562.5 3066.64   586.2 3077.86
#Mann= 3, -1 ,  0
       0     0.1       0  286.71   0.045       0   298.9     0.1       0
Bank Sta=286.71,298.9
XS Rating Curve= 0 ,0
Exp/Cntr(USF)=0,0
Exp/Cntr=0.3,0.1

Type RM Length L Ch R = 1 ,331     ,86.2,89.3,90.8
XS GIS Cut Line= 4
2317173.82755361647979.2241584982316918.66547364647866.751399564
2316819.62229786647861.7153058812316529.20756211647967.473273235
#Sta/Elev= 30
       0 3060.38    45.5 3037.98    76.1  3020.4    99.9 3003.55   132.9 2986.33
   150.4  2979.8   163.7 2972.69   207.3  2957.3     216 2951.88   255.3 2939.08
   289.4 2920.31   313.4 2914.98   334.7  2907.4   337.4 2906.56   342.32907.368
   365.5 2921.91   380.3 2926.77   390.2 2938.59   395.9 2942.89   445.5 2966.23
   455.2 2968.06   479.6 2980.24     505 2995.24   513.7 2998.76   530.7 3013.43
   594.5 3041.27   603.1 3047.31   626.8 3058.62   641.4 3070.79   687.1 3094.06
#Mann= 3, -1 ,  0
       0     0.1       0   334.7   0.045       0   342.3     0.1       0
Bank Sta=334.7,342.3
XS Rating Curve= 0 ,0
Exp/Cntr(USF)=0,0
Exp/Cntr=0.3,0.1

Type RM Length L Ch R = 1 ,241     ,80,80.6,81.3
XS GIS Cut Line= 4
2316939.73757082647856.0151467772316881.09838446647785.459224474
2316841.83386839647761.716315645 2316509.1227989647907.110799729
#Sta/Elev= 30
       0 2933.96     7.4 2929.81    40.1 2917.82    45.3 2914.97    55.6 2904.79
    58.5 2903.74    68.2 2901.42    92.8 2901.91  103.41 2897.64   106.8 2897.24
     113 2897.67   127.6 2900.02   136.3 2904.72   143.8 2906.84   156.9 2908.37
   178.7 2923.34   196.2 2921.16   204.9 2922.89   226.7 2941.55   248.6 2948.37
     266 2955.64   275.2  2956.4   292.2 2964.87   318.4 2974.21   372.4 3000.71
   393.7  3012.6     406 3016.48   418.8 3024.18   455.9 3041.94   500.7 3071.31
#Mann= 3, -1 ,  0
       0     0.1       0  103.41   0.045       0     113     0.1       0
Bank Sta=103.41,113
XS Rating Curve= 0 ,0
Exp/Cntr(USF)=0,0
Exp/Cntr=0.3,0.1

Type RM Length L Ch R = 1 ,161     ,7.6,6.2,6.9
XS GIS Cut Line= 4
 2316968.3770536647835.765483267 2316947.0391683647755.934686848
2316919.09276797647745.4874309122316566.90929353647807.146576657
#Sta/Elev= 30
       0 2926.07    15.3  2917.8    52.4 2904.74    67.6 2895.41    83.9 2891.14
   91.87 2891.33    98.5 2891.33     107 2890.19   111.3 2893.35   123.6 2893.22
   131.7 2896.98   143.9 2897.33   157.1 2902.98   160.1 2903.39   168.2 2899.02
   188.5 2905.73   212.9    2909   233.2 2923.75   241.3 2923.98   253.5 2919.82
   261.6 2920.82   269.7 2925.32   280.6 2934.62     290 2939.95   334.7  2951.4
   377.4 2966.11   395.6 2974.89   408.5 2977.24   452.5 2992.18     470 2999.46
#Mann= 3, -1 ,  0
       0     0.1       0   91.87   0.045       0    98.5     0.1       0
Bank Sta=91.87,98.5
XS Rating Curve= 0 ,0
Exp/Cntr(USF)=0,0
Exp/Cntr=0.3,0.1

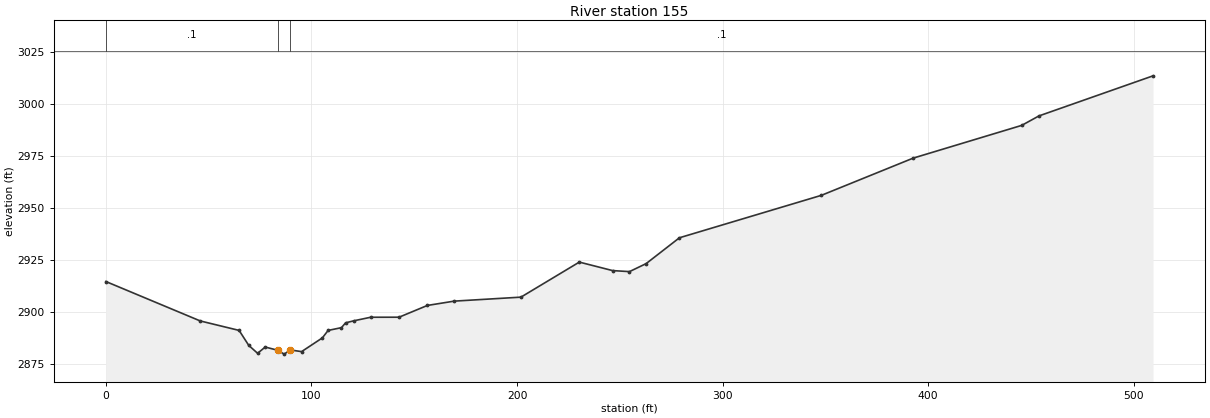
Type RM Length L Ch R = 1 ,155     ,,,
XS GIS Cut Line= 4
 2316979.8069811647808.5405385532316961.93842349647756.815039058
2316905.15909205647734.909984507 2316517.3012496647802.991719213
#Sta/Elev= 30
       0 2914.43    45.9 2895.47    64.8 2890.92    69.5  2883.7    73.8 2879.91
    77.5 2882.92    83.7 2881.34    86.7 2879.51    89.8  2881.5    95.2 2880.72
   105.3 2887.32   108.1 2890.91   114.6 2892.25   116.6 2894.56   120.6 2895.54
   128.8 2897.25   142.6 2897.27   156.4 2902.93   169.4    2905   201.9 2906.92
   230.3 2923.78   246.5 2919.69   254.7  2919.2   262.8 2923.05     279 2935.48
   348.1 2955.91   392.7 2973.79   445.5 2989.54   453.9  2994.1   509.4 3013.38
#Mann= 3, -1 ,  0
       0     0.1       0    83.7   0.045       0    89.8     0.1       0
Bank Sta=83.7,89.8
XS Rating Curve= 0 ,0
Exp/Cntr(USF)=0,0
Exp/Cntr=0.3,0.1
LCMann Table=0

Chan Stop Cuts=-1
Use User Specified Reach Order=0
Composite Channel Slope=5